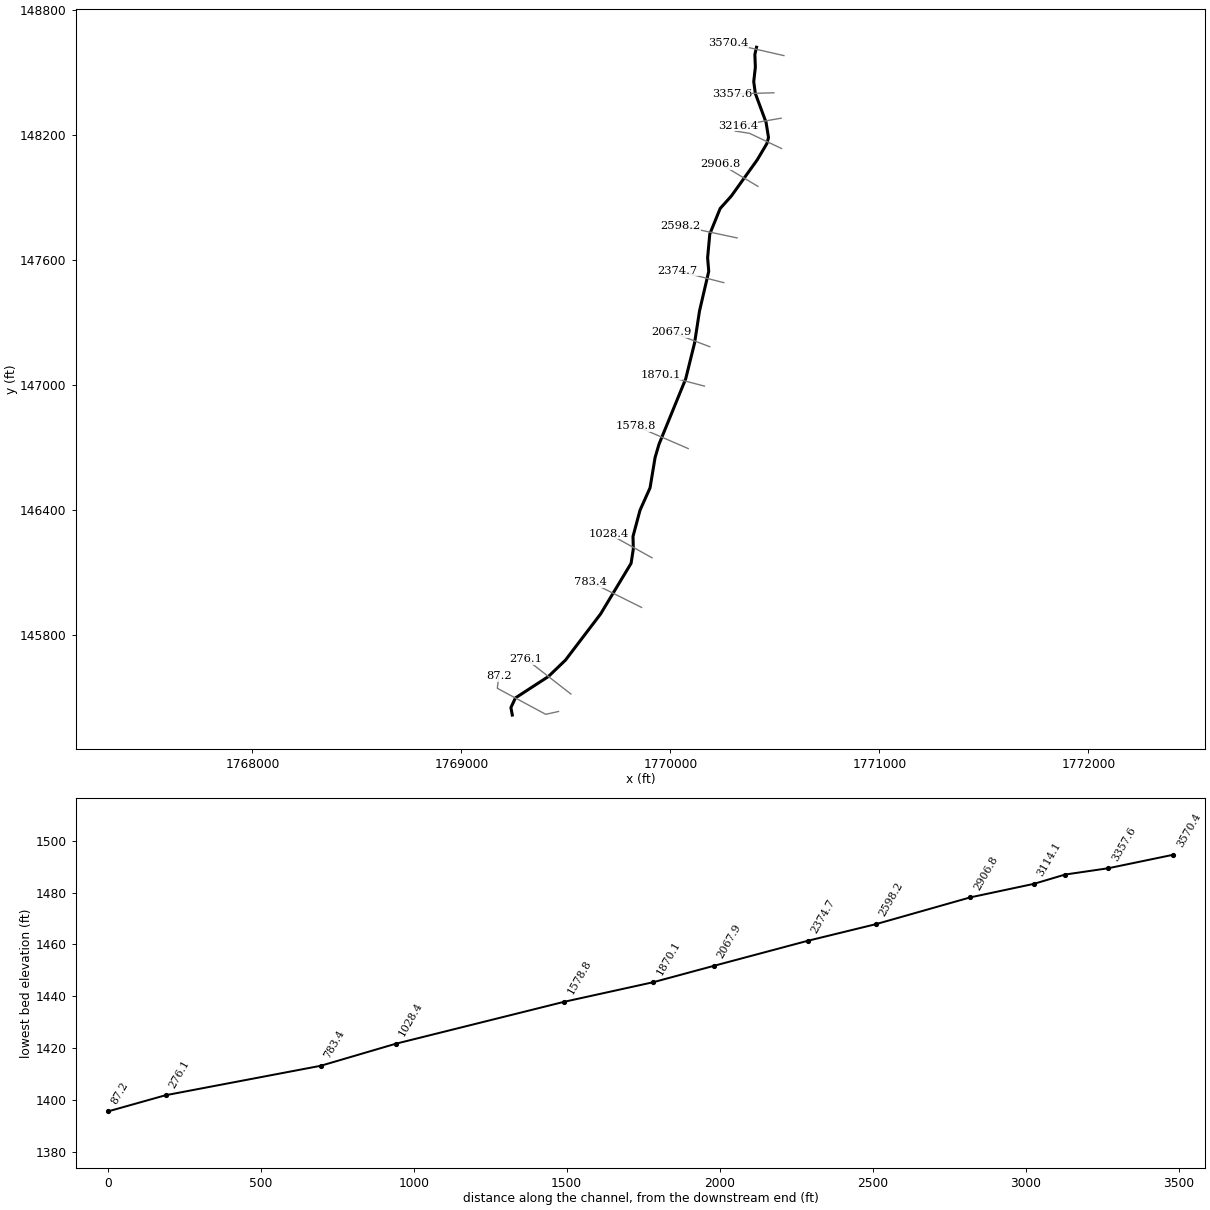
--- Daycamp Branch.prj (project) ---

Proj Title=Daycamp Branch
Current Plan=p01
Default Exp/Contr=0,0
English Units
Geom File=g01
Flow File=f01
Plan File=p01
BEGIN DESCRIPTION:
END DESCRIPTION:
DSS Export Rating Curves= 0
DSS Export Rating Curve Sorted= 0
DSS Export Volume Flow Curves= 0
DXF OffsetX= 0
DXF OffsetY= 0
DXF ScaleX= 0
DXF ScaleY= 0

--- Daycamp Branch.p01 (plan) ---

Plan Title=Floodplain
Program Version=4.00
Geom File=g01
Flow File=f01
K Sum by GR=0
Std Step Tol=0.01
Critical Tol=0.01
Num of Std Step Trials=20
Max Error Tol=0.3
Flow Tol Ratio=0.001
Split Flow NTrial=30
Split Flow Tol=0.02
Split Flow Ratio=0.02
Log Output Level=0
Friction Slope Method=1
Unsteady Friction Slope Method=2
Unsteady Bridges Friction Slope Method=1
Global Log Level=0
CheckData=False
Run HTab=0
Run UNet=0
Run PostProcess=0
UNET Theta=0
UNET Theta Warmup=0
UNET ZTol=0
UNET ZSATol=0
UNET MxIter=0
UNET MaxInSteps=0
UNET DtIC=0
UNET DtMin=0
UNET MaxCRTS=0
UNET WFStab=0
UNET SFStab=0
UNET WFX=0
UNET SFX=0
UNET DSS MLevel=0
UNET DZMax Abort=0
UNET Convert EG Bridges=0
UNET Use Existing IB Tables=0
UNET Froude Limit=0
UNET Froude Power=0
Write IC File=0
Echo Input=False
Echo Output=False
Write Detailed=0

--- Daycamp Branch.f01 (steady flow) ---

Flow Title=NFF Regression Equation
Program Version=4.00
Number of Profiles=1
Profile Names=P100yr
River Rch & RM=Daycamp Branch,Main      ,3570.4
619.6729
River Rch & RM=Daycamp Branch,Main      ,3216.4
635.1608
River Rch & RM=Daycamp Branch,Main      ,2374.7
689.9130
River Rch & RM=Daycamp Branch,Main      ,276.1
763.2750
Boundary for River Rch & Prof#=Daycamp Branch,Main      ,1
Up Type=0
Dn Type=3
Dn Slope=0.030087

--- Daycamp Branch.g01 (geometry) ---

Geom Title=Geometry
Program Version=4.00

River Reach=Daycamp Branch  ,Main
Reach XY= 30
     1770412.515      148619.563     1770404.506      148584.979
     1770406.831      148523.956     1770399.053      148454.658
     1770406.796       148397.55     1770458.097      148259.134
     1770469.712      148186.538     1770462.312      148157.995
     1770415.508      148079.097     1770291.882      147906.037
     1770238.379      147846.219     1770188.766      147723.764
     1770178.361      147609.864     1770183.762      147544.993
     1770139.644      147355.076     1770115.858      147200.924
     1770073.462      147029.277     1769945.682      146715.873
     1769927.053      146652.396     1769902.904      146506.814
     1769854.755      146399.021     1769821.295      146273.548
     1769822.869      146214.271     1769812.192      146144.886
      1769666.32      145902.195     1769498.403      145681.057
      1769416.56      145602.201     1769258.817      145499.531
     1769237.091      145453.243     1769243.745      145417.358

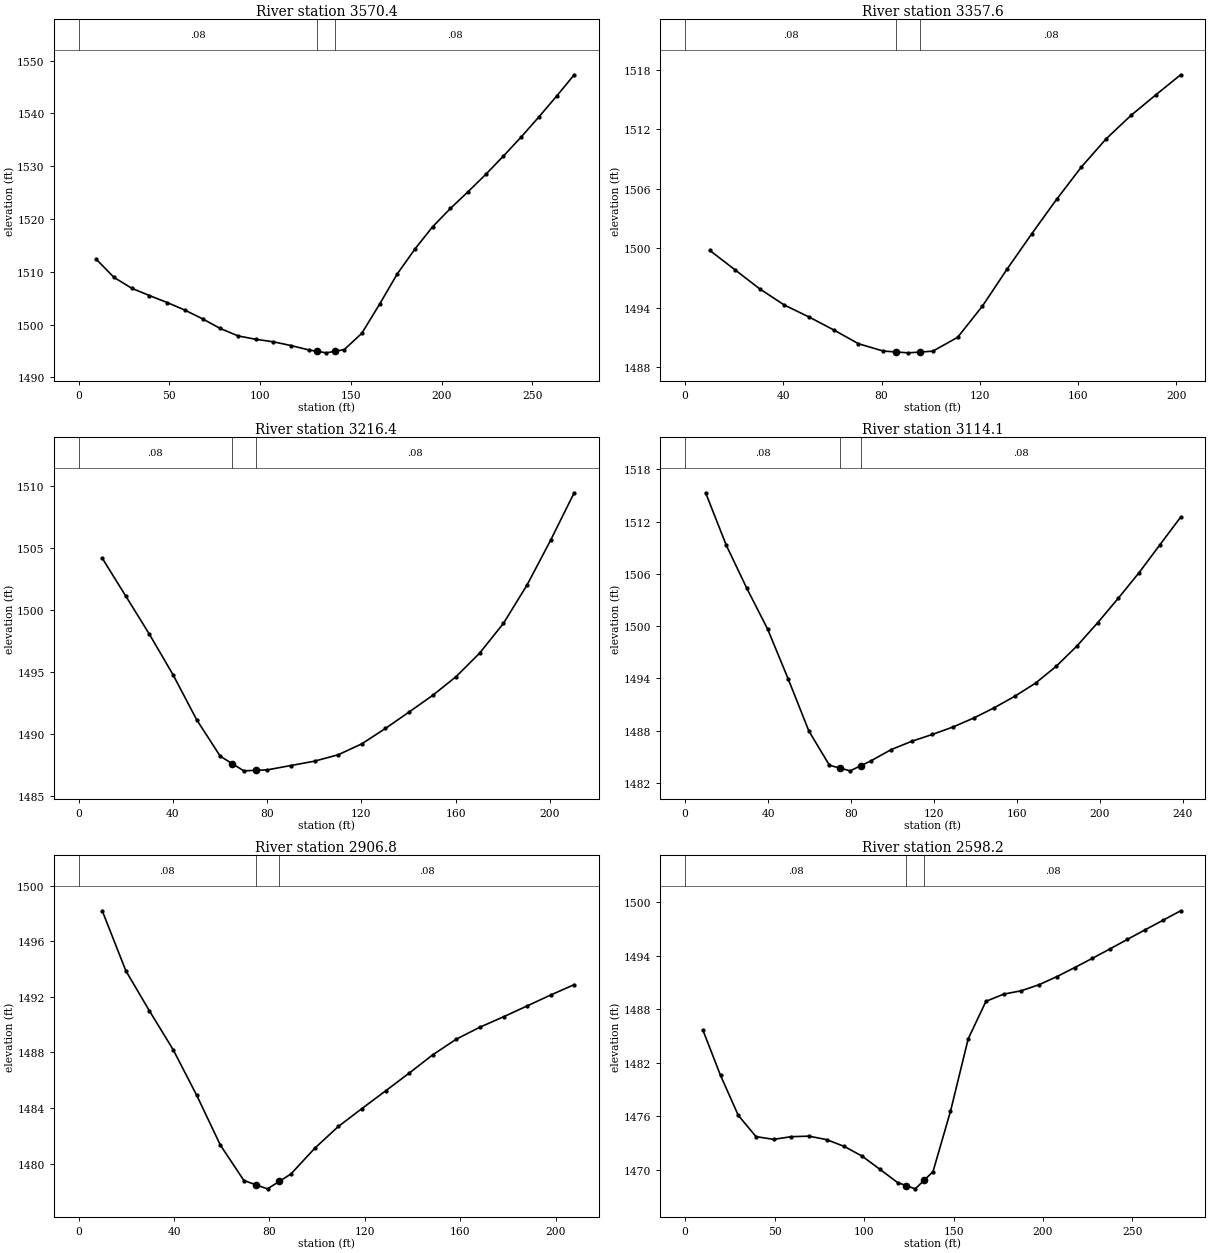
Type RM Length L Ch R = 1 ,3570.4  ,207.9,212.9,218
XS GIS Cut Line= 3
     1770543.328      148579.403     1770410.259       148609.82
     1770277.279      148640.616
#Sta/Elev= 30
     9.8 1512.35    19.5 1508.94    29.3 1506.88      39  1505.5    48.8 1504.18
    58.5 1502.75    68.3 1501.09      78 1499.27    87.8 1497.86    97.5 1497.22
   107.3 1496.74     117 1496.03   126.8  1495.2   131.5 1494.93   136.5 1494.65
   141.5 1494.96   146.3 1495.26     156 1498.35   165.8 1503.87   175.5 1509.58
   185.3 1514.33     195 1518.53   204.8    1522   214.5 1525.16   224.3 1528.46
     234 1531.92   243.8 1535.54   253.5 1539.32   263.3 1543.27     273 1547.33
#Mann= 3 , 0 , 0
       0     .08       0   131.5    .045       0   141.5     .08       0
Bank Sta=131.5,141.5
XS Rating Curve= 0 ,0
Exp/Cntr=0.3,0.1

Type RM Length L Ch R = 1 ,3357.6  ,138.2,141.2,144.1
XS GIS Cut Line= 2
     1770495.571      148401.005     1770293.882      148395.554
#Sta/Elev= 22
    10.1 1499.77    20.2 1497.84    30.3 1495.91    40.4 1494.26    50.4 1493.06
    60.5 1491.75    70.6 1490.35    80.7 1489.61    85.8 1489.52    90.8 1489.43
    95.8 1489.51   100.9  1489.6     111    1491   121.1 1494.16   131.1 1497.88
   141.2 1501.47   151.3 1504.94   161.4 1508.21   171.5 1511.06   181.6 1513.42
   191.7 1515.49   201.8 1517.52
#Mann= 3 , 0 , 0
       0     .08       0    85.8    .045       0    95.8     .08       0
Bank Sta=85.8,95.8
XS Rating Curve= 0 ,0
Exp/Cntr=0.3,0.1

Type RM Length L Ch R = 1 ,3216.4  ,114.7,102.3,89.8
XS GIS Cut Line= 2
     1770530.094      148279.265     1770322.955      148242.925
#Sta/Elev= 23
      10 1504.15      20 1501.09      30 1498.02    40.1 1494.73    50.1 1491.11
    60.1 1488.17    65.1 1487.58    70.1 1486.99    75.1 1487.03    80.1 1487.07
    90.1 1487.42   100.1 1487.77   110.2 1488.29   120.2 1489.17   130.2 1490.41
   140.2 1491.73   150.2 1493.07   160.2 1494.59   170.2 1496.49   180.3 1498.89
   190.3 1501.98   200.3 1505.59   210.3 1509.42
#Mann= 3 , 0 , 0
       0     .08       0    65.1    .045       0    75.1     .08       0
Bank Sta=65.1,75.1
XS Rating Curve= 0 ,0
Exp/Cntr=0.3,0.1

Type RM Length L Ch R = 1 ,3114.1  ,209.3,207.4,205.4
XS GIS Cut Line= 3
     1770531.911      148133.904     1770379.282      148206.585
     1770310.236      148217.487
#Sta/Elev= 26
     9.9  1515.3    19.9 1509.26    29.8 1504.32    39.8 1499.66    49.7 1493.95
    59.7 1487.96    69.6 1484.03    74.6 1483.71    79.6 1483.39    84.6 1483.96
    89.5 1484.52    99.4 1485.83   109.4 1486.79   119.3 1487.57   129.3 1488.43
   139.2 1489.45   149.2 1490.64   159.1 1491.96   169.1 1493.47     179 1495.39
     189 1497.72     199 1500.39     209 1503.22     219 1506.15     229 1509.33
     239  1512.5
#Mann= 3 , 0 , 0
       0     .08       0    74.6    .045       0    84.6     .08       0
Bank Sta=74.6,84.6
XS Rating Curve= 0 ,0
Exp/Cntr=0.3,0.1

Type RM Length L Ch R = 1 ,2906.8  ,301.8,308.5,315.2
XS GIS Cut Line= 2
     1770419.256      147952.203     1770241.189      148059.407
#Sta/Elev= 23
     9.9  1498.2    19.8 1493.88    29.7 1490.99    39.6 1488.21    49.5 1484.92
    59.4 1481.34    69.3 1478.78    74.2 1478.48    79.2 1478.18    84.2 1478.72
    89.1 1479.26      99  1481.1   108.9 1482.67   118.8 1483.96   128.7 1485.23
   138.6 1486.51   148.5 1487.83   158.4 1488.96   168.3 1489.82   178.2 1490.57
   188.1 1491.35     198 1492.14   207.8 1492.88
#Mann= 3 , 0 , 0
       0     .08       0    74.2    .045       0    84.2     .08       0
Bank Sta=74.2,84.2
XS Rating Curve= 0 ,0
Exp/Cntr=0.3,0.1

Type RM Length L Ch R = 1 ,2598.2  ,224.4,223.6,222.8
XS GIS Cut Line= 2
     1770319.321      147705.089     1770048.585      147763.233
#Sta/Elev= 30
     9.9 1485.67    19.8 1480.56    29.7 1476.09    39.6  1473.7    49.4 1473.39
    59.3 1473.69    69.2 1473.75    79.1 1473.36      89 1472.59    98.9 1471.51
   108.8 1470.04   118.7 1468.55   123.6  1468.2   128.6 1467.84   133.6 1468.81
   138.5 1469.76   148.3 1476.54   158.2 1484.67   168.1 1488.87     178 1489.68
   187.9 1490.06   197.8 1490.74   207.7 1491.64   217.6 1492.65   227.5 1493.69
   237.4 1494.75   247.2 1495.83   257.1  1496.9     267 1497.96   276.9 1499.03
#Mann= 3 , 0 , 0
       0     .08       0   123.6    .045       0   133.6     .08       0
Bank Sta=123.6,133.6
XS Rating Curve= 0 ,0
Exp/Cntr=0.3,0.1

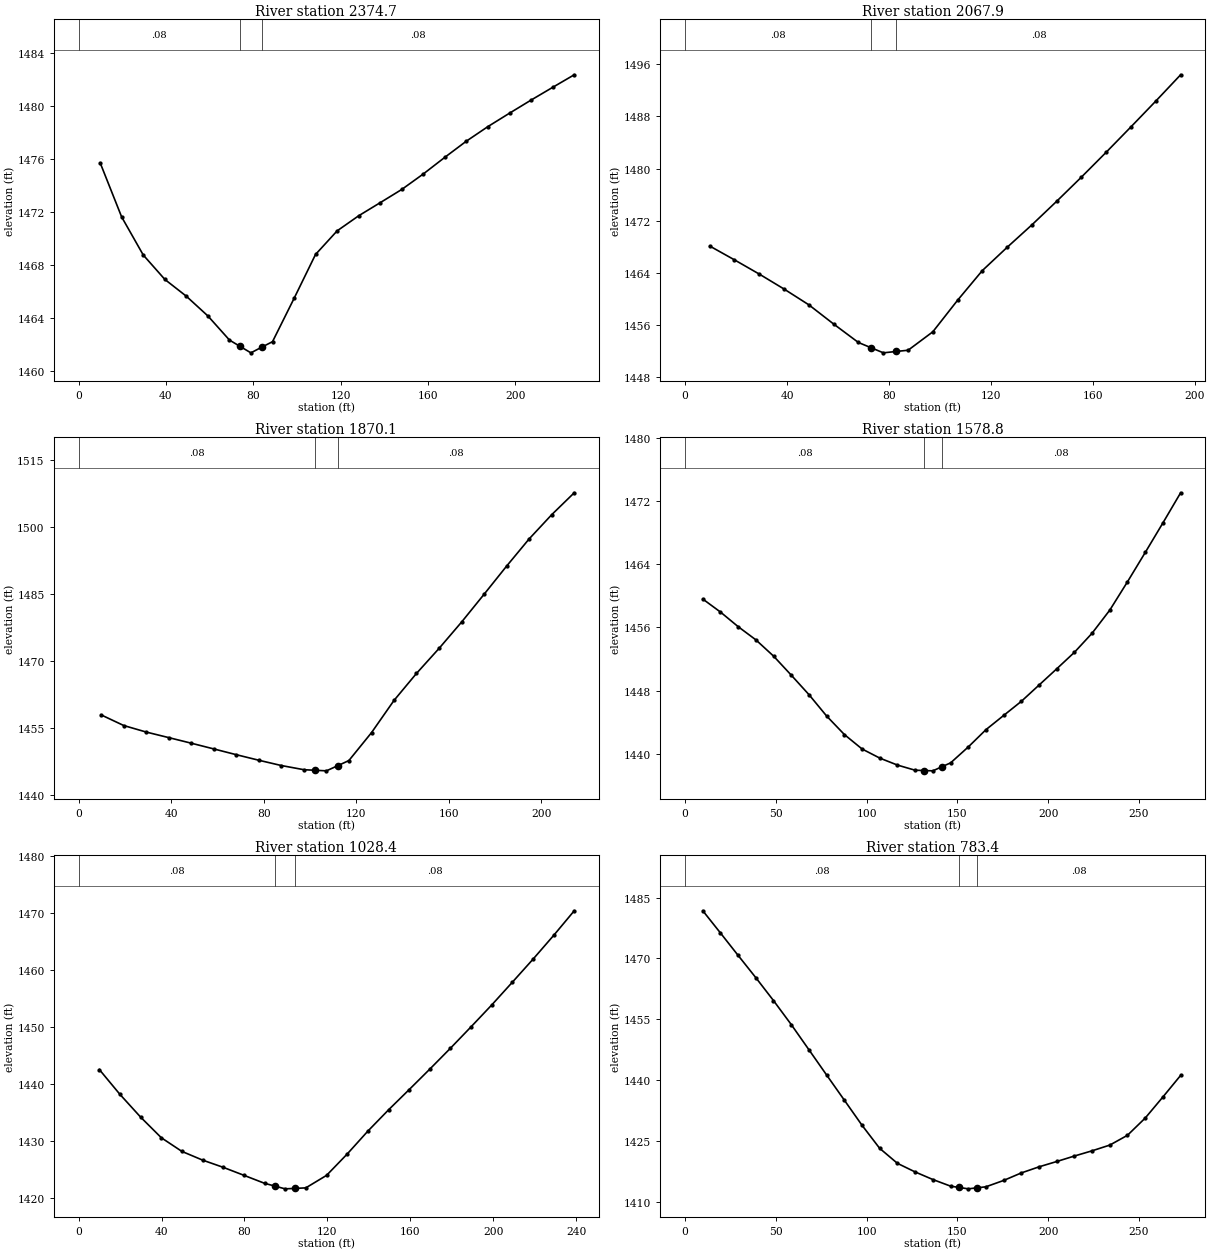
Type RM Length L Ch R = 1 ,2374.7  ,309.1,306.8,304.4
XS GIS Cut Line= 2
     1770255.725      147490.681     1770035.866      147547.009
#Sta/Elev= 25
     9.9 1475.69    19.7 1471.63    29.6 1468.76    39.5 1466.92    49.3 1465.66
    59.2 1464.17    69.1 1462.35    73.9 1461.88    78.9 1461.39    83.9 1461.82
    88.8 1462.23    98.7  1465.5   108.5  1468.8   118.4 1470.58   128.3 1471.72
   138.1  1472.7     148  1473.7   157.9 1474.87   167.8 1476.13   177.6 1477.34
   187.5 1478.44   197.4 1479.45   207.2 1480.43   217.1 1481.39     227 1482.34
#Mann= 3 , 0 , 0
       0     .08       0    73.9    .045       0    83.9     .08       0
Bank Sta=73.9,83.9
XS Rating Curve= 0 ,0
Exp/Cntr=0.3,0.1

Type RM Length L Ch R = 1 ,2067.9  ,195.6,197.8,200
XS GIS Cut Line= 2
     1770188.496      147183.606     1770006.794      147252.652
#Sta/Elev= 22
     9.7 1468.11    19.4 1465.99    29.2 1463.79    38.9  1461.5    48.6 1459.08
    58.3 1456.14      68 1453.31    72.8 1452.53    77.8 1451.72    82.8 1451.93
    87.5 1452.12    97.2 1454.95   106.9 1459.79   116.6 1464.34   126.3  1467.9
   136.1 1471.38   145.8 1474.99   155.5  1478.7   165.2 1482.51   174.9  1486.4
   184.7 1490.38   194.4  1494.4
#Mann= 3 , 0 , 0
       0     .08       0    72.8    .045       0    82.8     .08       0
Bank Sta=72.8,82.8
XS Rating Curve= 0 ,0
Exp/Cntr=0.3,0.1

Type RM Length L Ch R = 1 ,1870.1  ,294.3,291.3,288.2
XS GIS Cut Line= 2
     1770163.057      146994.636     1769955.918      147049.147
#Sta/Elev= 24
     9.7 1457.95    19.5 1455.56    29.2  1454.1    38.9 1452.86    48.7  1451.6
    58.4 1450.32    68.2 1449.02    77.9 1447.78    87.6  1446.6    97.4 1445.66
   102.1 1445.54   107.1 1445.41   112.1 1446.59   116.8 1447.71   126.6 1453.98
   136.3 1461.18     146 1467.22   155.8 1472.85   165.5 1478.73   175.2 1484.94
     185 1491.29   194.7 1497.36   204.5 1502.81   214.2  1507.7
#Mann= 3 , 0 , 0
       0     .08       0   102.1    .045       0   112.1     .08       0
Bank Sta=102.1,112.1
XS Rating Curve= 0 ,0
Exp/Cntr=0.3,0.1

Type RM Length L Ch R = 1 ,1578.8  ,553.3,550.4,547.3
XS GIS Cut Line= 3
     1770085.461      146695.205     1769960.173      146749.383
     1769834.886      146803.561
#Sta/Elev= 30
     9.8 1459.59    19.5 1457.95    29.3 1456.09      39 1454.43    48.8 1452.36
    58.5 1449.96    68.3 1447.48      78 1444.78    87.8 1442.43    97.5 1440.61
   107.3 1439.45     117 1438.57   126.7 1437.92   131.5 1437.88   136.5 1437.84
   141.5 1438.36   146.3 1438.85     156 1440.86   165.8 1443.06   175.5 1444.85
   185.3 1446.65     195  1448.7   204.8 1450.77   214.5 1452.85   224.2 1455.26
     234  1458.2   243.7 1461.77   253.5 1465.49   263.2 1469.22     273 1473.05
#Mann= 3 , 0 , 0
       0     .08       0   131.5    .045       0   141.5     .08       0
Bank Sta=131.5,141.5
XS Rating Curve= 0 ,0
Exp/Cntr=0.3,0.1

Type RM Length L Ch R = 1 ,1028.4  ,243.2,245,247
XS GIS Cut Line= 2
     1769912.309      146171.529     1769703.353      146287.818
#Sta/Elev= 26
      10 1442.56    19.9 1438.22    29.9 1434.22    39.9  1430.6    49.8 1428.21
    59.8 1426.68    69.7 1425.42    79.7 1424.02    89.7 1422.61    94.6 1422.13
    99.6 1421.64   104.6 1421.72   109.6 1421.81   119.6    1424   129.5 1427.72
   139.5 1431.75   149.5 1435.49   159.4 1439.02   169.4 1442.63   179.4 1446.31
   189.3 1450.05   199.3 1453.89   209.2 1457.86   219.2 1461.91   229.2  1466.1
   239.1 1470.41
#Mann= 3 , 0 , 0
       0     .08       0    94.6    .045       0   104.6     .08       0
Bank Sta=94.6,104.6
XS Rating Curve= 0 ,0
Exp/Cntr=0.3,0.1

Type RM Length L Ch R = 1 ,783.4   ,511.3,507.3,503.5
XS GIS Cut Line= 3
     1769862.289      145933.381       1769740.2      145994.426
     1769618.111      146055.471
#Sta/Elev= 30
     9.8 1481.75    19.5 1476.28    29.2 1470.76      39 1465.24    48.7 1459.61
    58.5 1453.68    68.2 1447.49      78 1441.22    87.8 1434.99    97.5 1428.82
   107.2 1423.14     117 1419.43   126.7 1417.32   136.5 1415.44   146.3  1413.8
     151 1413.48     156 1413.14     161  1413.4   165.7 1413.64   175.5 1415.21
   185.2 1417.06     195 1418.57   204.8 1419.89   214.5 1421.24   224.2 1422.52
     234 1423.94   243.7 1426.35   253.5 1430.61   263.2 1435.79     273 1441.13
#Mann= 3 , 0 , 0
       0     .08       0     151    .045       0     161     .08       0
Bank Sta=151,161
XS Rating Curve= 0 ,0
Exp/Cntr=0.3,0.1

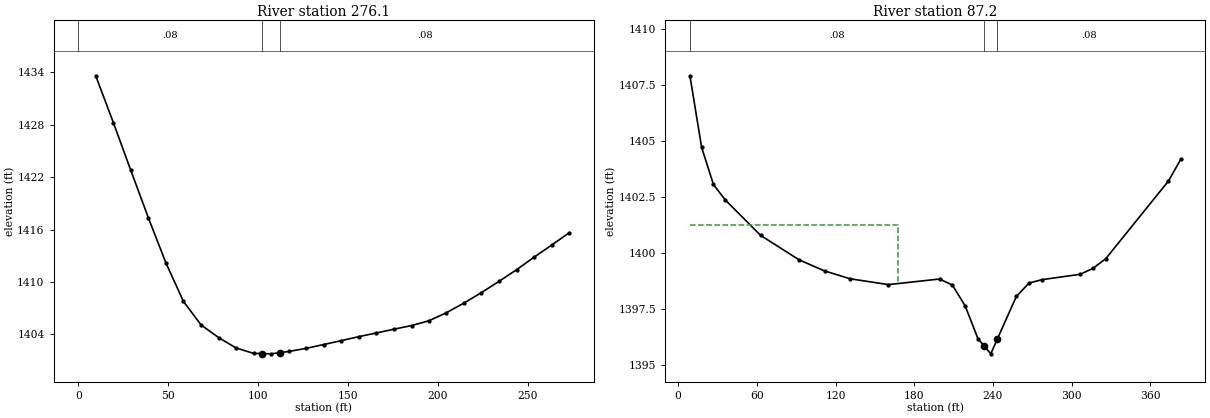
Type RM Length L Ch R = 1 ,276.1   ,185,188.9,192.3
XS GIS Cut Line= 3
     1769524.148      145518.195      1769416.56      145602.201
     1769308.972      145686.208
#Sta/Elev= 30
     9.7 1433.62    19.5 1428.26    29.2 1422.79      39 1417.33    48.8 1412.14
    58.5 1407.76    68.3 1405.07      78 1403.63    87.7 1402.44    97.5 1401.81
   102.2 1401.79   107.3 1401.76   112.2  1401.9     117 1402.03   126.8 1402.39
   136.5 1402.83   146.2 1403.27     156 1403.73   165.7 1404.15   175.5 1404.58
   185.3    1405     195 1405.55   204.7 1406.47   214.5 1407.58   224.2 1408.78
     234 1410.07   243.8 1411.41   253.5 1412.84   263.3 1414.23     273 1415.63
#Mann= 3 , 0 , 0
       0     .08       0   102.2    .045       0   112.2     .08       0
Bank Sta=102.2,112.2
XS Rating Curve= 0 ,0
Exp/Cntr=0.3,0.1

Type RM Length L Ch R = 1 ,87.2    ,73.6,87.2,101.1
XS GIS Cut Line= 4
     1769465.097      145434.502     1769403.772      145420.875
     1769172.103      145545.794     1769178.917      145602.576
#Sta/Elev= 24
       9  1407.9    17.9 1404.71    26.9 1403.05    35.9 1402.36    62.8 1400.78
    92.1 1399.69   111.6 1399.19   131.1 1398.84   160.3 1398.58   199.3 1398.83
     209 1398.56   218.8 1397.63   228.5 1396.17   233.3 1395.84   238.3 1395.49
   243.3 1396.15   257.8 1398.05   267.5 1398.65   277.3  1398.8   306.5 1399.04
   316.3 1399.31     326 1399.74   373.7  1403.2   383.2 1404.18
#Mann= 3 , 0 , 0
       9     .08       0   233.3    .045       0   243.3     .08       0
#XS Ineff= 2 , 0
          167.79 1401.23
Permanent Ineff=
       F       F
Bank Sta=233.3,243.3
XS Rating Curve= 0 ,0
Exp/Cntr=0.3,0.1

Chan Stop Cuts=-1
Use User Specified Reach Order=0